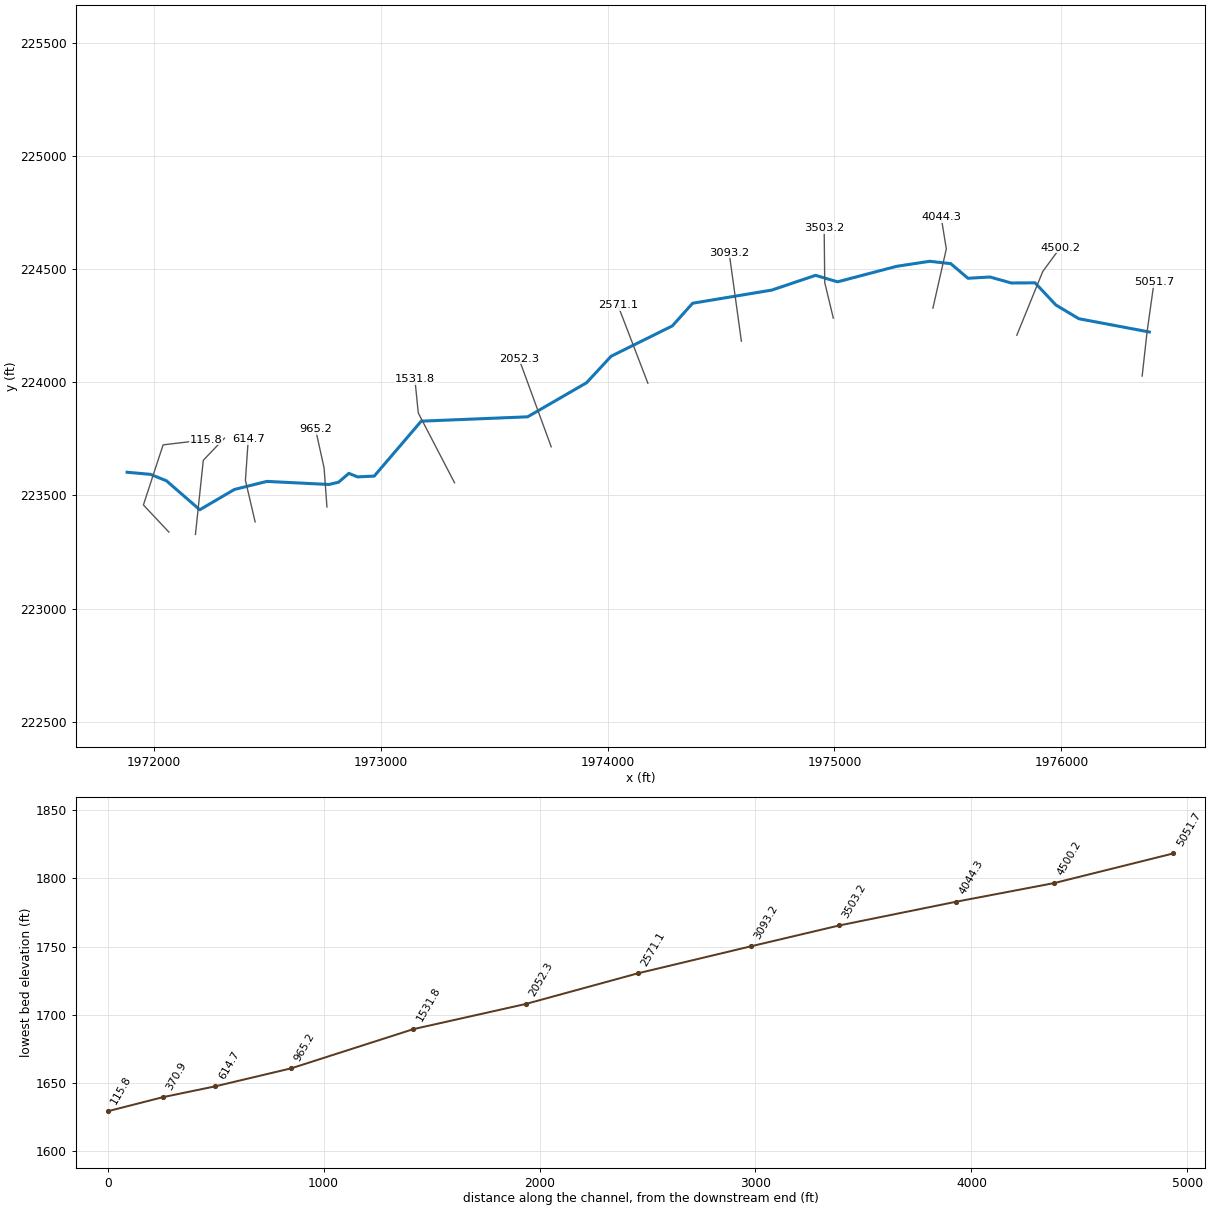
--- SUNRISEBR.prj (project) ---

Proj Title=SUNRISEBR
Current Plan=p01
Default Exp/Contr=0,0
English Units
Geom File=g01
Flow File=f01
Plan File=p01
BEGIN DESCRIPTION:
END DESCRIPTION:
DSS Export Rating Curves= 0
DSS Export Rating Curve Sorted= 0
DSS Export Volume Flow Curves= 0
DXF OffsetX= 0
DXF OffsetY= 0
DXF ScaleX= 0
DXF ScaleY= 0

--- SUNRISEBR.p01 (plan) ---

Plan Title=Floodplain
Program Version=4.00
Geom File=g01
Flow File=f01
K Sum by GR=0
Std Step Tol=0.01
Critical Tol=0.01
Num of Std Step Trials=20
Max Error Tol=0.3
Flow Tol Ratio=0.001
Split Flow NTrial=30
Split Flow Tol=0.02
Split Flow Ratio=0.02
Log Output Level=0
Friction Slope Method=1
Unsteady Friction Slope Method=2
Unsteady Bridges Friction Slope Method=1
Global Log Level=0
CheckData=False
Run HTab=0
Run UNet=0
Run PostProcess=0
UNET Theta=0
UNET Theta Warmup=0
UNET ZTol=0
UNET ZSATol=0
UNET MxIter=0
UNET MaxInSteps=0
UNET DtIC=0
UNET DtMin=0
UNET MaxCRTS=0
UNET WFStab=0
UNET SFStab=0
UNET WFX=0
UNET SFX=0
UNET DSS MLevel=0
UNET DZMax Abort=0
UNET Convert EG Bridges=0
UNET Use Existing IB Tables=0
UNET Froude Limit=0
UNET Froude Power=0
Write IC File=0
Echo Input=False
Echo Output=False
Write Detailed=0

--- SUNRISEBR.f01 (steady flow) ---

Flow Title=2010 USGS WV Regression Equation
Program Version=4.00
Number of Profiles=1
Profile Names=P100yr
River Rch & RM=SUNRISEBR,Main      ,5051.7
511.7075
River Rch & RM=SUNRISEBR,Main      ,4044.3
558.7874
River Rch & RM=SUNRISEBR,Main      ,370.9
601.7534
River Rch & RM=SUNRISEBR,Main      ,115.8
604.8945
Boundary for River Rch & Prof#=SUNRISEBR,Main      ,1
Up Type=0
Dn Type=3
Dn Slope=0.036884

--- SUNRISEBR.g01 (geometry) ---

Geom Title=LiDAR
Program Version=4.10

River Reach=SUNRISEBR       ,Main
Reach XY= 30
     1976388.032      224221.902     1976077.252      224280.484
     1975975.861      224341.231     1975884.303      224439.059
     1975779.442      224438.365     1975685.692      224464.754
      1975588.47      224459.198     1975512.379      224523.838
      1975419.72      224534.198     1975273.887      224511.976
      1975013.49        224443.5     1974916.702      224472.146
     1974723.939      224407.038     1974374.634      224348.909
     1974285.166       224248.72     1974015.291      224114.791
     1973906.959      223997.576     1973647.171      223847.146
     1973178.088      223827.919      1972971.02      223585.277
     1972897.236      223581.805     1972859.041       223597.43
     1972813.902      223558.368     1972771.208      223548.237
      1972497.93       223561.84     1972354.701       223526.25
     1972201.858      223436.556     1972055.221      223564.444
     1971984.529      223593.101     1971881.731      223602.183

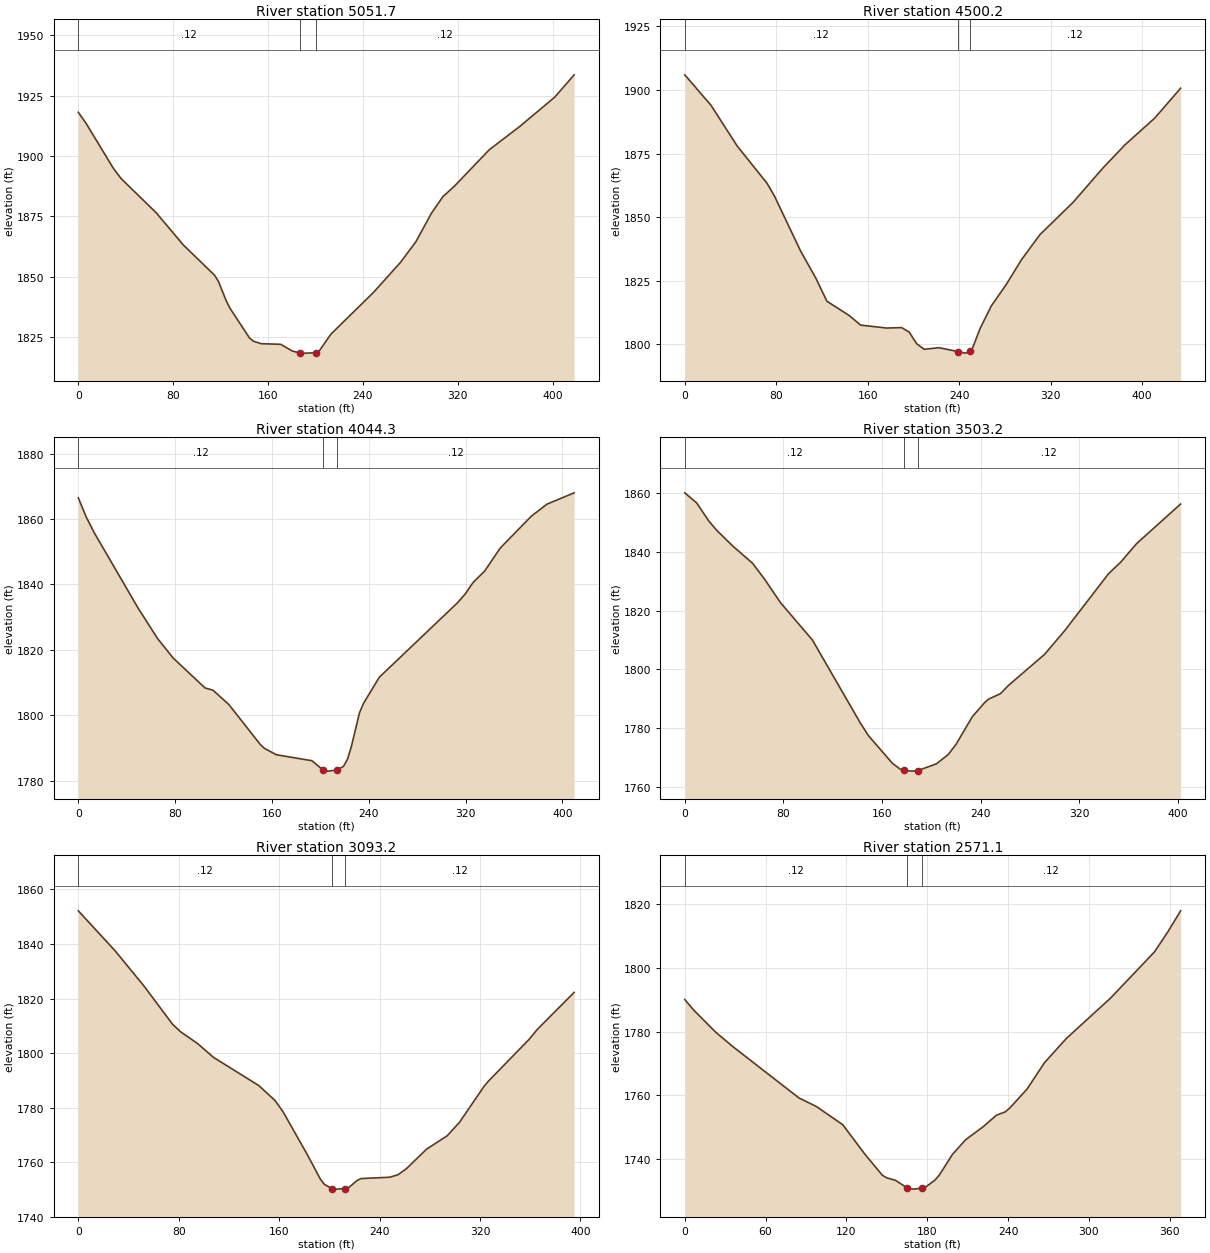
Type RM Length L Ch R = 1 ,5051.7  ,556.8,551.5,545
XS GIS Cut Line= 3
     1976356.374      224027.172     1976378.073      224222.801
     1976408.888       224441.89
#Sta/Elev= 30
       0 1918.07     6.6 1913.44    29.5 1894.91    36.1 1890.61    65.6  1876.5
    88.6  1863.1   114.8 1850.64   118.1 1848.09   124.7 1840.02   127.9  1836.9
   144.3 1824.64   147.6 1823.28   154.2 1822.23   170.6 1821.99   180.4 1819.22
     187 1818.36   193.6 1818.33   200.1 1818.55   203.3 1819.36   213.1 1826.25
   248.9 1843.48   271.7 1855.94   284.7  1864.5   297.7 1876.24   307.4 1883.13
   317.2 1887.51   346.5 1902.55   372.5 1912.31   401.8 1924.38   418.1 1933.59
#Mann= 3 ,-1 , 0
       0     .12       0     187    .045       0   200.1     .12       0
Bank Sta=187,200.1
XS Rating Curve= 0 ,0
Exp/Cntr=0.3,0.1

Type RM Length L Ch R = 1 ,4500.2  ,450.7,455.8,457.9
XS GIS Cut Line= 3
     1975803.863      224207.702     1975918.368      224489.559
     1975995.124      224593.998
#Sta/Elev= 30
       0 1905.91    22.9 1893.97    45.8 1877.98      72  1863.3    78.5 1858.26
   101.4 1836.63   114.5 1826.18   124.3 1817.01   143.9 1811.37   153.8 1807.62
   176.6 1806.46   189.7 1806.64   196.3 1804.88   202.8 1800.34   209.4 1798.11
   222.4 1798.74   238.8 1797.24   245.4 1796.61  249.321797.263   251.9 1798.78
   258.4 1806.31   268.2 1815.18   281.3  1823.6   294.4 1833.19   310.7 1843.14
   339.9 1855.92   365.8 1869.31   385.2 1878.45   411.2 1888.94   433.8 1900.65
#Mann= 3 ,-1 , 0
       0     .12       0   238.8    .045       0  249.32     .12       0
Bank Sta=238.8,249.32
XS Rating Curve= 0 ,0
Exp/Cntr=0.3,0.1

Type RM Length L Ch R = 1 ,4044.3  ,533.4,541.1,546.5
XS GIS Cut Line= 3
     1975433.925      224327.239     1975493.065      224588.964
     1975470.415      224728.635
#Sta/Elev= 30
       0 1866.49     6.5 1860.67    13.1 1855.86    49.1 1832.96    65.4 1823.49
    78.5 1817.44   104.7 1808.34   111.3 1807.64   124.4 1803.26   150.5 1790.99
   153.8 1789.85   163.6  1787.9   193.1 1786.06  202.341783.186   206.2 1782.88
   213.8  1783.2   219.2 1784.36   222.5 1786.56   225.8 1790.59   232.3 1800.64
   235.6 1803.54   248.7 1811.59   313.3 1834.36   319.8  1837.1   326.2 1840.57
   335.9 1844.12   348.7 1851.14   374.4 1860.89   387.3 1864.57   409.8 1868.04
#Mann= 3 ,-1 , 0
       0     .12       0  202.34    .045       0   213.8     .12       0
Bank Sta=202.34,213.8
XS Rating Curve= 0 ,0
Exp/Cntr=0.3,0.1

Type RM Length L Ch R = 1 ,3503.2  ,408.5,410,411.9
XS GIS Cut Line= 3
      1974994.78      224283.199     1974957.032      224440.486
     1974954.515       224680.82
#Sta/Elev= 30
       0 1859.93     9.7 1856.48    19.4 1850.41    25.9 1847.21    38.8 1841.92
      55 1836.02    64.7 1830.63    77.6 1822.67   103.5 1809.99   142.3 1781.87
   148.8 1777.61   168.2 1768.23   174.7 1766.15     178 1765.73   184.5  1765.5
  188.971765.688     204 1767.96   213.7 1771.15   220.2 1774.74   233.2 1783.99
     243 1788.67   246.2 1789.89   255.9 1791.76   262.4 1794.55   291.7 1805.09
   307.9 1813.07   343.6 1832.46   353.4 1836.35   366.4  1842.7   402.1 1856.14
#Mann= 3 ,-1 , 0
       0     .12       0     178    .045       0  188.97     .12       0
Bank Sta=178,188.97
XS Rating Curve= 0 ,0
Exp/Cntr=0.3,0.1

Type RM Length L Ch R = 1 ,3093.2  ,516,522.1,526.7
XS GIS Cut Line= 2
      1974589.61      224181.277     1974535.503      224572.607
#Sta/Elev= 30
       0 1852.17    29.4 1837.47    52.2 1824.68    75.1 1810.59    81.6  1807.8
    94.7 1803.64   107.7 1798.47   143.7 1788.15   156.7 1782.67   163.2 1778.46
   182.8 1762.51   192.6 1754.02   195.9 1751.98   201.91750.395   205.7 1750.18
   212.2 1750.39   215.5 1750.77     222 1753.33   225.3 1754.06   248.1 1754.54
   254.7 1755.47   261.2 1757.61   277.5 1764.85   293.8 1769.71   303.6 1774.64
   323.2 1787.83   326.5 1789.66   359.1 1805.06   365.7 1808.74     395 1822.29
#Mann= 3 ,-1 , 0
       0     .12       0   201.9    .045       0   212.2     .12       0
Bank Sta=201.9,212.2
XS Rating Curve= 0 ,0
Exp/Cntr=0.3,0.1

Type RM Length L Ch R = 1 ,2571.1  ,518.5,518.8,518
XS GIS Cut Line= 2
     1974177.338      223995.647       1974045.5      224339.353
#Sta/Elev= 30
       0 1790.06     6.5  1786.8    22.8 1779.85    35.8 1775.22    84.7 1759.13
    97.7 1756.42   117.3 1750.69   133.6 1741.48   146.6 1734.83   149.9 1733.99
   156.4 1733.22   165.31730.773   169.4 1730.44   175.9 1730.73   179.2 1731.21
   185.7 1733.27     189 1734.89   198.7 1741.36   208.5 1745.98   221.5 1750.06
   231.3 1753.67   237.8 1754.72   241.1 1755.87   254.1 1761.91   267.1 1770.24
   283.4 1777.88     316 1790.48   348.6    1805   358.4  1811.2   368.1 1817.96
#Mann= 3 ,-1 , 0
       0     .12       0   165.3    .045       0   175.9     .12       0
Bank Sta=165.3,175.9
XS Rating Curve= 0 ,0
Exp/Cntr=0.3,0.1

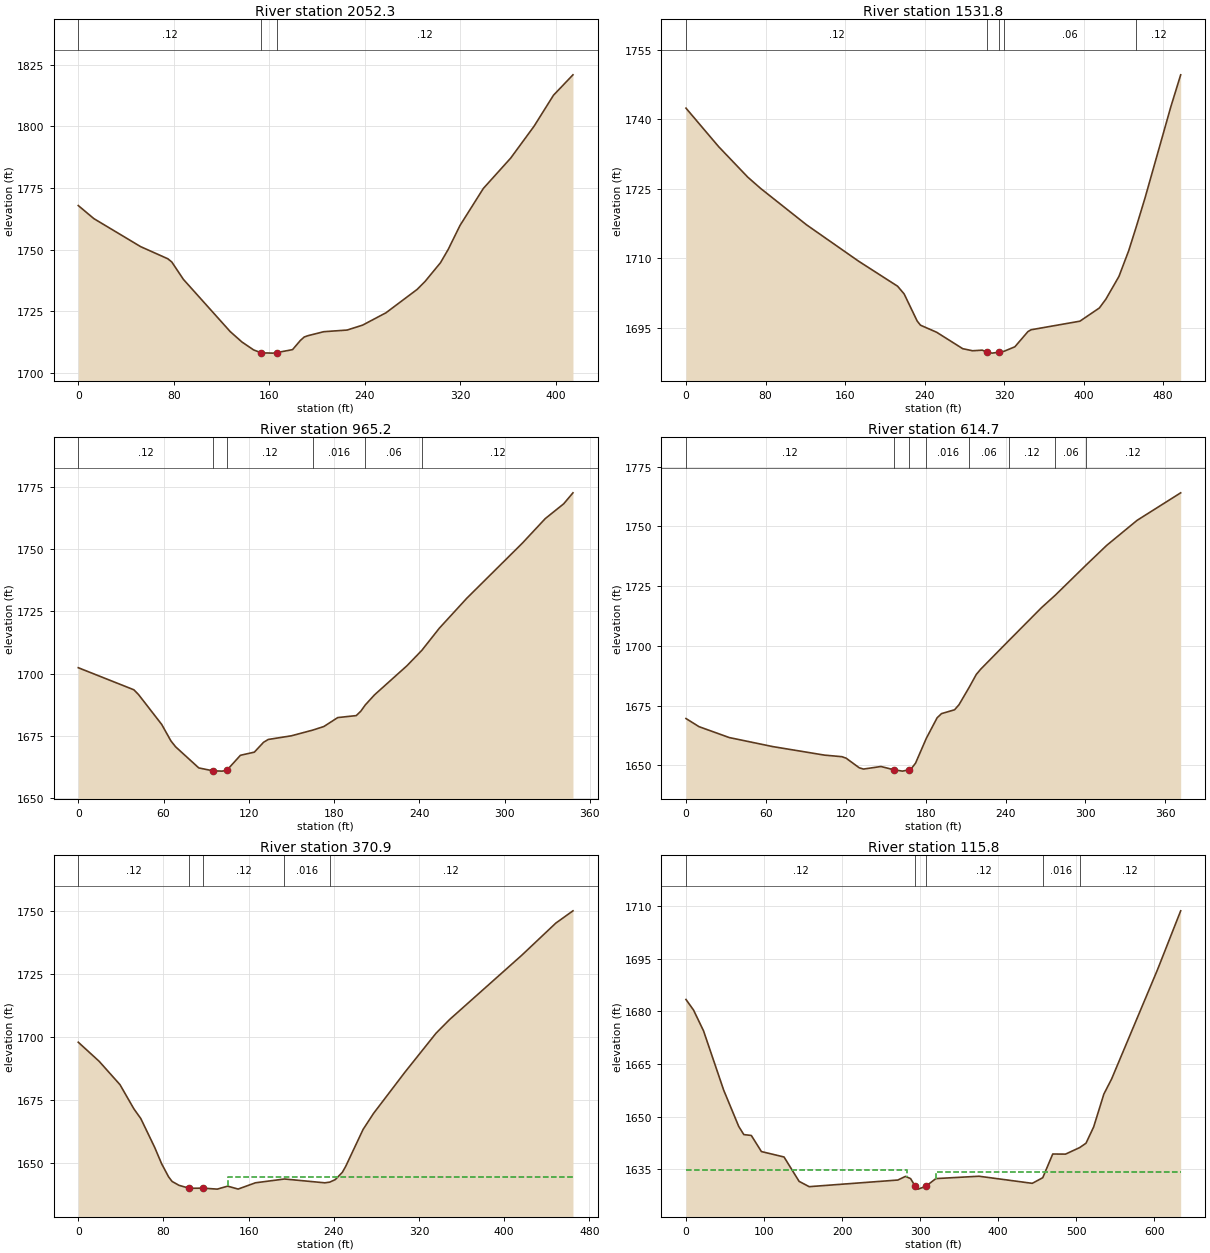
Type RM Length L Ch R = 1 ,2052.3  ,516.7,520.6,522.6
XS GIS Cut Line= 2
     1973751.237      223714.561     1973608.945      224103.985
#Sta/Elev= 30
       0 1767.86    13.1 1762.55    52.2 1751.21    75.1 1746.26    78.4 1744.96
    88.1 1737.92   127.3 1716.75   137.1 1712.53   146.9 1709.31   153.4 1708.11
   163.2 1707.99   166.5 1708.22   179.6 1709.41   186.1 1713.11   189.4 1714.54
   192.6 1715.08   205.7 1716.68   225.3 1717.35   238.3 1719.35   257.9 1724.36
     284 1733.84   290.6 1737.04   303.6 1744.69   310.1 1750.12   319.9 1759.76
   339.5 1774.81   362.4 1787.11     382 1800.05   398.3 1812.64   414.6  1820.9
#Mann= 3 ,-1 , 0
       0     .12       0   153.4    .045       0   166.5     .12       0
Bank Sta=153.4,166.5
XS Rating Curve= 0 ,0
Exp/Cntr=0.3,0.1

Type RM Length L Ch R = 1 ,1531.8  ,573.4,566.6,555.6
XS GIS Cut Line= 3
     1973325.025      223555.906     1973165.222      223864.187
     1973150.122      224013.924
#Sta/Elev= 30
       0 1742.38    32.8 1734.09    62.2 1727.49    75.3 1725.03   121.2 1717.23
   173.6 1709.38   212.9 1703.97   219.5  1702.3   232.6 1696.46   235.9 1695.57
   252.2 1694.04   278.4  1690.5   288.3 1690.05   298.1 1690.18  302.821689.741
   307.9 1689.54   314.5 1689.73  320.071689.946   330.9 1690.91     344 1694.18
   347.2 1694.58   396.3 1696.43   415.9 1699.28   422.5  1701.2   435.6 1706.09
   445.4 1711.63  453.071716.829   461.8 1722.99   487.9 1742.76   497.7 1749.57
#Mann= 5 ,-1 , 0
       0     .12       0  302.82    .045       0   314.5     .12       0
  320.07     .06       0  453.07     .12       0
Bank Sta=302.82,314.5
XS Rating Curve= 0 ,0
Exp/Cntr=0.3,0.1

Type RM Length L Ch R = 1 ,965.2   ,346.2,350.5,353.2
XS GIS Cut Line= 3
     1972762.568      223448.951     1972749.985      223621.337
     1972712.236      223792.465
#Sta/Elev= 30
       0 1702.34    39.1 1693.48    42.4 1691.56    58.7 1679.56    65.2 1672.93
    68.5 1670.56    84.8 1662.08    94.6 1660.93   101.1 1660.79   104.4 1661.05
   114.1 1667.15   123.9 1668.42   130.4 1672.39   133.7 1673.51     150 1674.99
     1651677.276   172.8 1678.71   182.6 1682.31   195.6  1683.1   198.8 1684.86
  201.991687.402   208.5 1691.46   231.3 1703.14  241.791709.341     254 1718.17
   273.4 1730.26   312.4 1752.34   328.6 1762.25   341.6 1768.21   348.1 1772.61
#Mann= 6 ,-1 , 0
       0     .12       0    94.6    .045       0   104.4     .12       0
     165    .016       0  201.99     .06       0  241.79     .12       0
Bank Sta=94.6,104.4
XS Rating Curve= 0 ,0
Exp/Cntr=0.3,0.1

Type RM Length L Ch R = 1 ,614.7   ,251.1,243.8,235.3
XS GIS Cut Line= 3
     1972445.971      223382.954      1972403.19      223566.665
     1972415.772      223749.117
#Sta/Elev= 30
       0 1669.64     9.8 1666.24    32.5 1661.68      65 1657.92   104.1 1654.33
   117.1 1653.68   120.3 1653.04   130.1 1649.04   133.3  1648.5   146.4 1649.58
   156.1  1648.2   162.6 1647.64  167.331648.178   169.1 1648.61   172.4 1650.99
  180.521661.409   188.6 1669.96   191.9  1671.7   201.7  1673.3     205  1675.4
  212.741682.766     218 1688.09   221.3 1690.27  242.351702.197     267 1716.03
  277.391721.267  300.421733.822     316 1742.11   338.8 1752.56   371.5 1764.06
#Mann= 8 ,-1 , 0
       0     .12       0   156.1    .045       0  167.33     .12       0
  180.52    .016       0  212.74     .06       0  242.35     .12       0
  277.39     .06       0  300.42     .12       0
Bank Sta=156.1,167.33
XS Rating Curve= 0 ,0
Exp/Cntr=0.3,0.1

Type RM Length L Ch R = 1 ,370.9   ,258.4,255.1,248.5
XS GIS Cut Line= 3
       1972182.8      223327.589     1972217.522       223655.28
     1972310.838      223752.936
#Sta/Elev= 30
       0  1697.9    19.6 1690.34    39.2 1681.06    52.2  1671.5    58.7 1667.65
    71.8 1656.17    78.3  1649.7    84.8 1644.54    88.1  1642.7    94.6 1641.16
   104.4 1639.97   117.4 1640.04   130.5 1639.65   140.3 1640.83   150.1 1639.67
   166.4 1642.16  193.671643.665   231.6 1642.15   236.21642.432   241.4 1643.43
     248 1646.31   251.2 1648.71   267.5 1663.33   277.3 1669.67   306.7 1685.97
     336 1701.47   348.8 1706.92   416.4 1732.34   448.5 1745.13   464.6    1750
#Mann= 5 ,-1 , 0
       0     .12       0   104.4    .045       0   117.4     .12       0
  193.67    .016       0   236.2     .12       0
#XS Ineff= 2 , 0
                          140.35         1644.36
Permanent Ineff=
       F       F
Bank Sta=104.4,117.4
XS Rating Curve= 0 ,0
Exp/Cntr=0.3,0.1

Type RM Length L Ch R = 1 ,115.8   ,109.1,115.8,119.5
XS GIS Cut Line= 4
     1972065.825      223337.956     1971953.485      223457.759
     1972040.308      223723.259     1972229.052      223745.908
#Sta/Elev= 30
       0 1683.35     9.7 1680.33    22.5 1674.41    48.3 1657.53    67.6 1647.19
    74.1 1644.88    83.7 1644.63    96.6 1640.05   125.6  1638.5   144.9 1631.56
   157.8 1630.05   271.4 1631.94   281.2 1632.98   287.7 1632.35  293.651630.147
   297.4 1629.35   307.2 1630.15   320.1 1632.35   375.4 1633.02   443.6    1631
  457.021632.607   469.8 1639.35   486.2 1639.32  504.481641.202   512.4 1642.42
   522.2 1647.05   535.3 1656.42   545.2 1660.71   604.2 1691.94   633.7  1708.6
#Mann= 5 ,-1 , 0
       0     .12       0  293.65    .045       0   307.2     .12       0
  457.02    .016       0  504.48     .12       0
#XS Ineff= 2 , 0
          283.18 1634.86  320.02         1634.19
Permanent Ineff=
       F       F
Bank Sta=293.65,307.2
XS Rating Curve= 0 ,0
Exp/Cntr=0.3,0.1

Chan Stop Cuts=-1
Use User Specified Reach Order=0
Composite Channel Slope=5